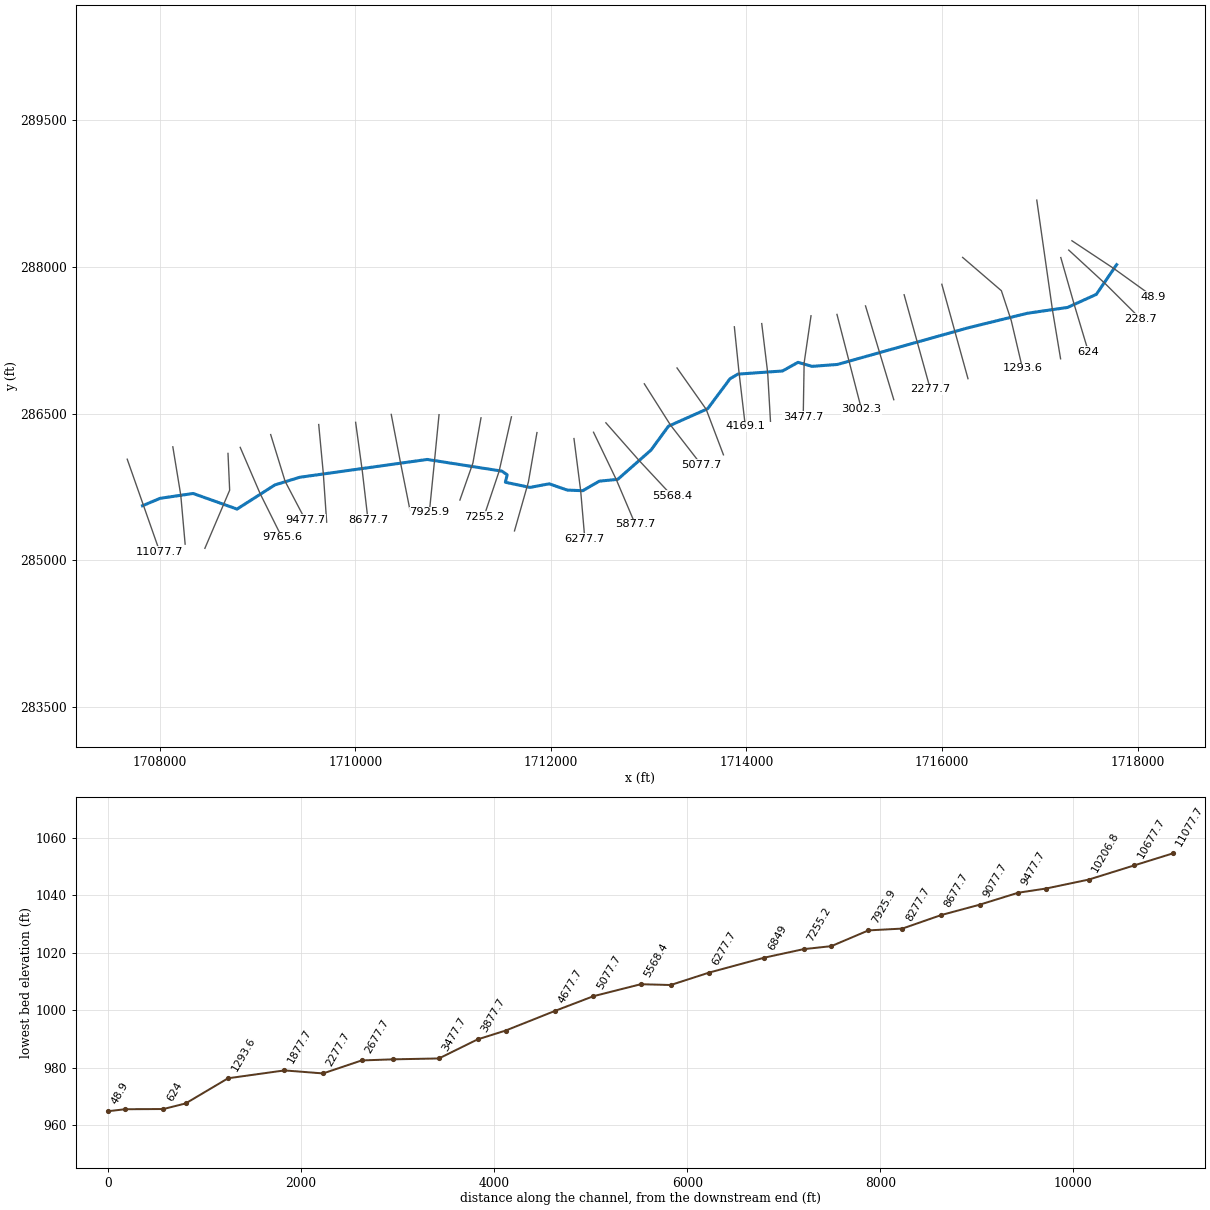
--- SimpsnFk.prj (project) ---

Proj Title=SimpsnFk
Current Plan=p01
Default Exp/Contr=0,0
English Units
Geom File=g01
Flow File=f01
Plan File=p01
BEGIN DESCRIPTION:
END DESCRIPTION:
DSS Export Rating Curves= 0
DSS Export Rating Curve Sorted= 0
DSS Export Volume Flow Curves= 0
DXF OffsetX= 0
DXF OffsetY= 0
DXF ScaleX= 0
DXF ScaleY= 0

--- SimpsnFk.p01 (plan) ---

Plan Title=Floodplain
Program Version=4.00
Geom File=g01
Flow File=f01
K Sum by GR=0
Std Step Tol=0.01
Critical Tol=0.01
Num of Std Step Trials=20
Max Error Tol=0.3
Flow Tol Ratio=0.001
Split Flow NTrial=30
Split Flow Tol=0.02
Split Flow Ratio=0.02
Log Output Level=0
Friction Slope Method=1
Unsteady Friction Slope Method=2
Unsteady Bridges Friction Slope Method=1
Global Log Level=0
CheckData=False
Run HTab=0
Run UNet=0
Run PostProcess=0
UNET Theta=0
UNET Theta Warmup=0
UNET ZTol=0
UNET ZSATol=0
UNET MxIter=0
UNET MaxInSteps=0
UNET DtIC=0
UNET DtMin=0
UNET MaxCRTS=0
UNET WFStab=0
UNET SFStab=0
UNET WFX=0
UNET SFX=0
UNET DSS MLevel=0
UNET DZMax Abort=0
UNET Convert EG Bridges=0
UNET Use Existing IB Tables=0
UNET Froude Limit=0
UNET Froude Power=0
Write IC File=0
Echo Input=False
Echo Output=False
Write Detailed=0

--- SimpsnFk.f01 (steady flow) ---

Flow Title=NFF Regression Equation
Program Version=4.00
Number of Profiles= 1
Profile Names=P100yr
River Rch & RM=SimpsnFk,Main            ,11077.7
734.7888
River Rch & RM=SimpsnFk,Main            ,10206.8
796.5905
River Rch & RM=SimpsnFk,Main            ,8277.7
  862.89
River Rch & RM=SimpsnFk,Main            ,7255.2
950.9706
River Rch & RM=SimpsnFk,Main            ,5077.7
1047.155
River Rch & RM=SimpsnFk,Main            ,1293.6
1153.284
River Rch & RM=SimpsnFk,Main            ,854.2
2470.048
River Rch & RM=SimpsnFk,Main            ,228.7
2475.595
River Rch & RM=SimpsnFk,Main            ,48.9
2481.133
Boundary for River Rch & Prof#=SimpsnFk,Main            , 1
Up Type= 3
Up Slope=0.010372
Dn Type= 1
Dn Known WS=976.43
DSS Import GetInterval= 0
DSS Import GetPeak= 0
DSS Import FillOption= 0

--- SimpsnFk.g01 (geometry) ---

Geom Title=USGS 3m DEM
Program Version=4.00

River Reach=SimpsnFk        ,Main
Reach XY= 30
     1707822.479      285558.042     1708002.712      285633.842
      1708340.19      285683.033     1708788.953      285523.768
     1709176.639      285770.951     1709429.932      285848.722
     1710734.063      286030.941     1711498.056       285911.47
     1711552.379      285874.326     1711533.859         285798.
     1711784.451      285745.273     1711982.577       285781.83
     1712167.139      285717.595     1712325.404      285711.638
     1712494.315      285808.971     1712683.608      285827.814
     1713023.074      286126.258       1713201.8      286370.739
      1713603.06      286549.508     1713831.213      286855.253
     1713911.448      286902.825     1714368.397      286935.069
      1714527.09      287023.507     1714670.622      286982.461
     1714929.372       287001.62     1716265.183       287375.71
     1716873.183      287525.022     1717284.098      287584.388
     1717578.308      287717.857     1717786.187      288021.677

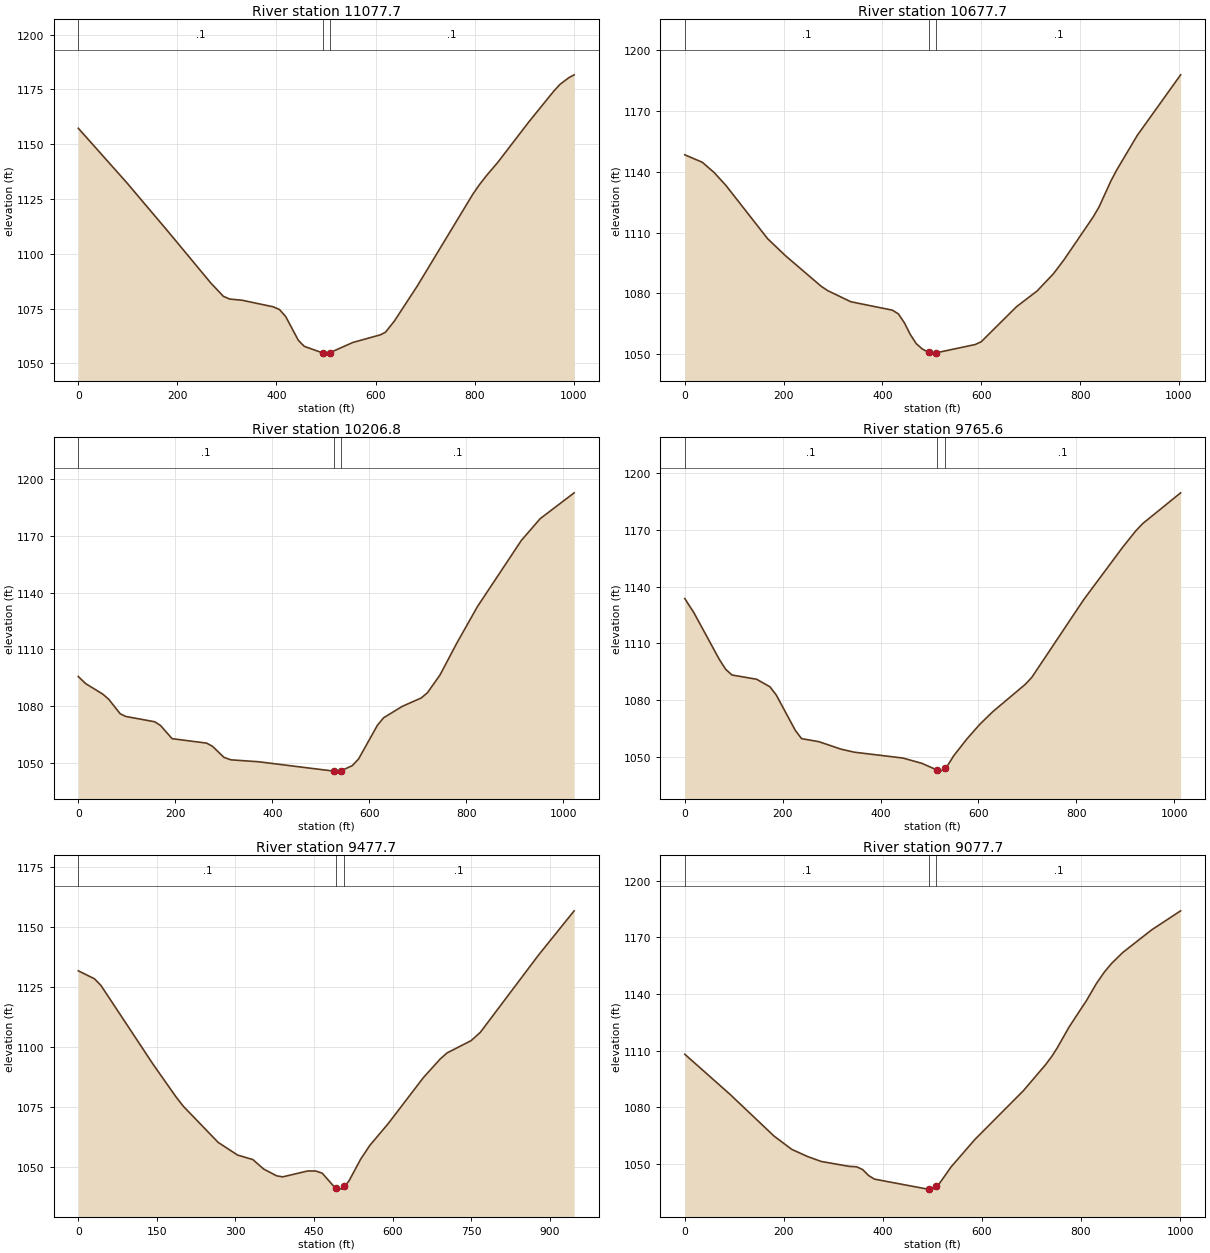
Type RM Length L Ch R = 1 ,11077.7 ,403.947,400,394.382
XS GIS Cut Line= 3
     1707665.868      286033.513     1707831.913      285561.359
     1707997.958      285089.205
#Sta/Elev= 30
       0 1157.23    97.9 1132.38   181.7 1109.99   267.7 1086.57   292.9 1080.55
   305.5 1079.32   330.6 1078.77   393.6 1075.77   406.2 1074.51   418.8 1071.28
   443.9  1060.6   451.7 1058.72   456.5 1057.71     493 1054.76   498.2 1054.64
     508 1054.87   554.1 1059.49     610 1063.01   620.1 1064.18   637.9 1069.22
   684.5 1085.34   795.8 1126.92   808.9 1131.23   824.1 1135.65   846.7 1141.64
   909.6 1160.16   959.9 1174.18   972.5 1177.29   990.7 1180.37    1001 1181.61
#Mann= 3 , 0 , 0
       0      .1       0     493    .045       0     508      .1       0
Bank Sta=493,508
XS Rating Curve= 0 ,0
Exp/Cntr=0.3,0.1

Type RM Length L Ch R = 1 ,10677.7 ,484.807,470.882,461.006
XS GIS Cut Line= 3
     1708132.318      286160.066      1708213.55       285665.94
     1708258.239      285165.233
#Sta/Elev= 30
       0 1148.43    35.3 1144.77    59.3  1139.7    83.4 1133.26   167.6    1107
   203.7 1098.59   275.9 1083.51   289.1 1081.34   336.1 1075.83   420.3 1071.67
   432.3 1069.82   444.4 1065.46   456.4 1059.66   468.4 1055.15   480.5 1052.53
   493.3 1050.85   504.5 1050.45   508.3 1050.58   587.9 1054.71   599.9 1056.08
   671.4  1073.4   712.9 1081.13   746.1 1089.67     768 1096.75   826.3 1117.64
   838.3 1122.63   862.1 1135.36     874 1140.87   915.8 1158.04  1003.5 1187.95
#Mann= 3 , 0 , 0
       0      .1       0   493.3    .045       0   508.3      .1       0
Bank Sta=493.3,508.3
XS Rating Curve= 0 ,0
Exp/Cntr=0.3,0.1

Type RM Length L Ch R = 1 ,10206.8 ,422.261,441.188,460.85
XS GIS Cut Line= 3
     1708696.598      286092.759     1708713.691      285716.713
     1708460.273      285122.857
#Sta/Elev= 30
       0 1095.59      15 1091.89    50.7 1086.23    62.6 1083.59    86.3  1075.9
    97.6 1074.48   157.6 1071.64   169.5 1069.66   193.3  1062.7   264.6 1060.34
   276.5 1058.66   300.3 1052.79   314.7 1051.49   371.6 1050.47   526.1 1045.53
   535.7 1045.51   541.1 1045.67   564.8 1048.42   577.7 1051.95   616.4 1069.74
   629.3 1073.77     668 1079.84   706.8 1084.25   719.7 1087.03   745.5 1096.42
     780  1113.2   822.9 1132.72   913.3  1167.7     952 1179.19  1022.1 1192.89
#Mann= 3 , 0 , 0
       0      .1       0   526.1    .045       0   541.1      .1       0
Bank Sta=526.1,541.1
XS Rating Curve= 0 ,0
Exp/Cntr=0.3,0.1

Type RM Length L Ch R = 1 ,9765.6  ,290.875,287.93,288.457
XS GIS Cut Line= 3
     1708821.625      286154.412     1709025.163      285682.052
     1709247.696      285235.735
#Sta/Elev= 30
       0 1133.75    18.8 1126.18    70.5 1101.55    83.5 1096.33    96.4 1093.29
   146.8 1091.04     174 1087.05   186.9  1082.7   225.7 1064.03   238.6  1059.6
   274.2 1057.98   319.4 1054.01   346.5 1052.42   445.5 1049.33   484.2 1046.55
   516.3 1042.89   523.2  1042.4   531.3 1043.98   535.8 1044.91   549.8 1050.65
   576.3  1059.4   602.8  1067.2   629.4 1073.89   695.7 1088.35     709 1092.03
   815.1 1133.19   894.7 1160.92   921.2 1169.51   935.6 1173.45  1013.1 1189.73
#Mann= 3 , 0 , 0
       0      .1       0   516.3    .045       0   531.3      .1       0
Bank Sta=516.3,531.3
XS Rating Curve= 0 ,0
Exp/Cntr=0.3,0.1

Type RM Length L Ch R = 1 ,9477.7  ,404.637,400,390.593
XS GIS Cut Line= 3
     1709133.295      286285.223     1709281.024      285807.163
     1709488.573      285411.888
#Sta/Elev= 30
       0 1131.91    30.7 1128.61    43.2 1125.82   142.6 1093.02   186.6 1079.36
   200.4 1075.49     267 1060.42   304.1 1055.14   333.3 1053.26   353.8 1049.32
   378.7 1046.48   390.3 1046.05   437.8  1048.5   453.3 1048.49   465.7 1047.59
   490.5 1041.45   492.9 1041.38   503.2 1040.94   507.9 1042.06   516.6 1044.28
   539.1 1053.41   556.5 1059.13   591.9 1068.29   658.6 1087.34   690.9 1095.15
   704.3 1097.72   750.1 1102.83   767.7 1106.29   878.6 1138.43   946.8 1156.91
#Mann= 3 , 0 , 0
       0      .1       0   492.9    .045       0   507.9      .1       0
Bank Sta=492.9,507.9
XS Rating Curve= 0 ,0
Exp/Cntr=0.3,0.1

Type RM Length L Ch R = 1 ,9077.7  ,399.044,400,401.063
XS GIS Cut Line= 3
     1709624.544      286387.815     1709671.431      285889.549
     1709705.855      285390.044
#Sta/Elev= 30
       0 1108.17    91.3 1086.95   180.3 1064.83     216 1057.81   248.2 1053.99
   275.7  1051.4   331.1 1048.84   347.2 1048.57   359.1 1047.12   371.1 1043.97
     383 1042.05   490.3 1036.76     493 1036.84   502.2 1037.09     508 1038.34
   514.1 1039.73   537.9 1048.58   585.5 1062.98   683.8 1088.91   728.3 1102.59
   741.2 1107.09   752.1 1111.57   775.9 1122.57   811.6 1136.81   830.7 1145.43
   847.3 1151.73   861.9 1156.29   884.2 1162.01   942.6 1174.01  1001.2 1184.11
#Mann= 3 , 0 , 0
       0      .1       0     493    .045       0     508      .1       0
Bank Sta=493,508
XS Rating Curve= 0 ,0
Exp/Cntr=0.3,0.1

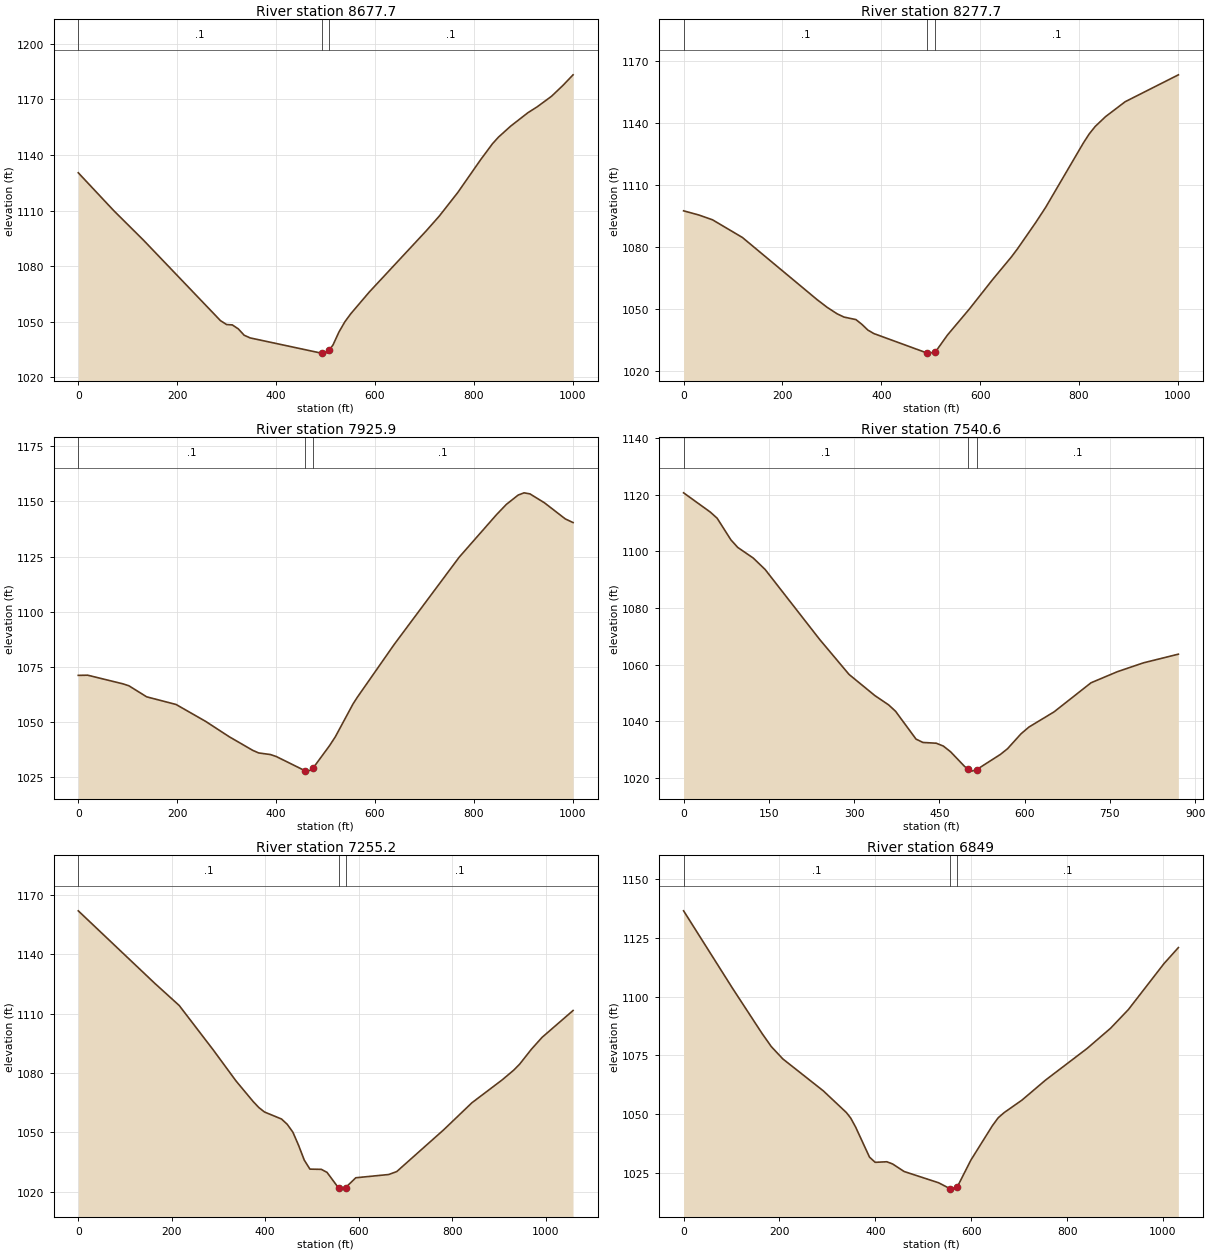
Type RM Length L Ch R = 1 ,8677.7  ,398.795,400,401.832
XS GIS Cut Line= 3
     1710002.146      286410.323     1710070.163       285914.34
     1710128.114      285417.229
#Sta/Elev= 30
       0 1130.39      72 1109.91     132 1094.03   287.7 1050.65     300 1048.55
   311.7 1048.35   323.7 1046.22   335.7 1042.77   347.7 1041.34   491.5 1033.13
   493.1 1033.16   503.4 1033.42   508.1 1034.93   515.4 1037.54   527.3 1044.46
   539.3 1049.99   551.3 1054.35   588.6 1066.02   703.7 1098.98   730.6 1107.09
   767.9 1119.77   814.2 1137.48   838.1 1146.06   850.1 1149.59   874.9 1155.55
   909.8 1162.79   928.5 1165.95   957.7 1171.68     981 1177.61  1001.1 1183.21
#Mann= 3 , 0 , 0
       0      .1       0   493.1    .045       0   508.1      .1       0
Bank Sta=493.1,508.1
XS Rating Curve= 0 ,0
Exp/Cntr=0.3,0.1

Type RM Length L Ch R = 1 ,8277.7  ,358.231,351.749,345.095
XS GIS Cut Line= 3
     1710366.365       286491.43     1710460.777      285999.919
     1710558.931       285509.12
#Sta/Elev= 30
       0 1097.45    30.8 1095.43    58.5  1093.1     119 1084.52     270  1054.4
   290.3 1050.67   310.6 1047.51   324.5 1045.93   348.7  1044.7   360.8 1042.38
   372.9  1039.6     385 1037.92     493 1028.45   493.1 1028.44   505.9 1028.79
     508 1029.22   513.4 1030.35   533.5 1037.12   578.5 1049.93   624.3 1063.86
   663.3 1075.14   675.4    1079   711.7 1091.54   732.4 1099.11   808.6 1130.29
   820.7 1134.78   832.8 1138.39   853.5  1143.1   893.3 1150.36    1001 1163.41
#Mann= 3 , 0 , 0
       0      .1       0     493    .045       0     508      .1       0
Bank Sta=493,508
XS Rating Curve= 0 ,0
Exp/Cntr=0.3,0.1

Type RM Length L Ch R = 1 ,7925.9  ,390.738,385.313,379.889
XS GIS Cut Line= 3
     1710855.218      286488.434     1710806.332      285990.327
     1710756.181      285492.344
#Sta/Elev= 30
       0 1071.18      19 1071.26    90.5 1067.33   102.5 1066.45   138.3 1061.46
   197.9 1057.99   257.6 1050.35   305.3 1043.39     353 1037.21   364.9 1036.04
   388.8 1035.31   400.7  1034.4   459.6 1027.88   460.4  1027.8   472.3 1028.31
   474.6 1029.06   508.1 1039.26     520 1043.34   555.8 1058.21   564.6 1061.28
   639.3 1085.24   770.6 1124.71   846.4 1144.05   866.1 1148.64   889.9 1152.85
   901.9 1153.87   913.8 1153.39   943.2 1149.34   985.4 1142.04    1001  1140.4
#Mann= 3 , 0 , 0
       0      .1       0   459.6    .045       0   474.6      .1       0
Bank Sta=459.6,474.6
XS Rating Curve= 0 ,0
Exp/Cntr=0.3,0.1

Type RM Length L Ch R = 1 ,7540.6  ,282.75,285.363,286.256
XS GIS Cut Line= 3
     1711284.626      286456.479     1711201.672      285993.999
     1711068.726      285616.054
#Sta/Elev= 30
       0 1120.71      47  1113.9    59.1 1111.71    83.2 1104.09    95.3  1101.4
   122.6 1097.64   143.5 1093.59   239.4 1068.86   291.1 1056.49   336.5 1049.02
   360.6 1045.74   372.9 1043.47   408.9 1033.63     421 1032.44   444.5 1032.17
   457.1 1031.15   469.9 1029.11   494.3 1023.97   500.5 1023.06   506.9  1022.3
   515.5 1022.82   557.3  1028.2   569.9 1030.22   593.6 1035.49   607.6 1037.89
   651.6 1043.23   716.8 1053.54   763.3 1057.47     809 1060.59   870.5 1063.66
#Mann= 3 , 0 , 0
       0      .1       0   500.5    .045       0   515.5      .1       0
Bank Sta=500.5,515.5
XS Rating Curve= 0 ,0
Exp/Cntr=0.3,0.1

Type RM Length L Ch R = 1 ,7255.2  ,401.827,406.246,407.483
XS GIS Cut Line= 3
     1711595.717      286466.373     1711469.662      285909.889
     1711314.205      285446.951
#Sta/Elev= 30
       0 1161.95   163.7  1125.3   215.9 1114.13   288.9 1091.62   337.6 1075.95
   374.1  1065.6   386.3 1062.54   398.5 1060.26     435 1056.71   447.2 1054.04
   459.3 1050.04   471.5 1043.41   483.7 1035.92   495.8 1031.38   520.2 1031.27
   532.4 1029.73   557.3 1021.77   568.9 1021.27   572.3 1022.09   593.9 1027.01
   664.4 1028.66   681.6 1030.15   781.8 1051.21   842.5 1064.94     907 1076.46
     932 1081.43   944.6 1084.45   969.6 1091.94   992.5 1097.97  1058.9 1111.56
#Mann= 3 , 0 , 0
       0      .1       0   557.3    .045       0   572.3      .1       0
Bank Sta=557.3,572.3
XS Rating Curve= 0 ,0
Exp/Cntr=0.3,0.1

Type RM Length L Ch R = 1 ,6849    ,562.462,571.329,579.262
XS GIS Cut Line= 3
     1711856.903      286305.472     1711769.476      285801.022
     1711627.097      285300.783
#Sta/Elev= 30
       0 1136.36   102.1  1103.5   163.7 1084.33   182.9 1078.78     207 1073.54
   291.4    1060   339.6 1050.78   348.6 1048.45   358.8 1044.65   387.8 1031.88
   399.6 1029.68   423.9 1029.92     436 1028.98   460.1 1025.78     532    1021
   556.2 1018.45   557.5 1018.31   569.9 1018.86   571.2 1019.37   599.3 1030.64
   643.9 1045.14   656.3 1048.59   668.6 1050.76   705.7 1056.05     755 1064.56
   841.5 1077.95   890.8 1086.58   927.9  1094.5  1001.9 1113.93  1032.1 1120.77
#Mann= 3 , 0 , 0
       0      .1       0   556.2    .045       0   571.2      .1       0
Bank Sta=556.2,571.2
XS Rating Curve= 0 ,0
Exp/Cntr=0.3,0.1

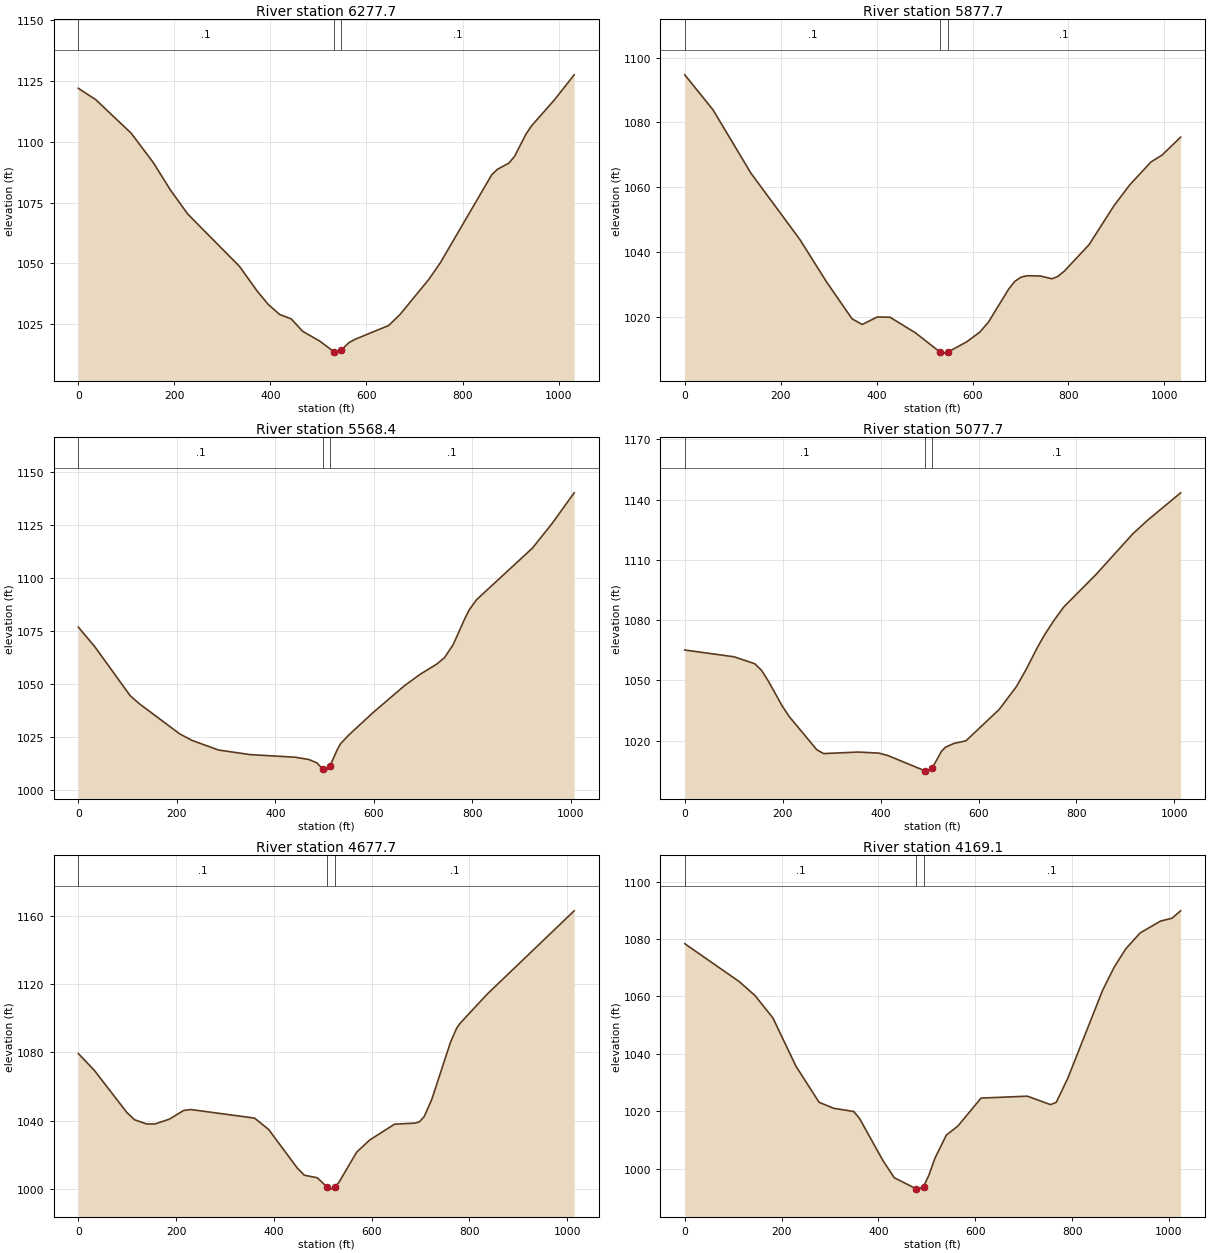
Type RM Length L Ch R = 1 ,6277.7  ,392.812,400,407.087
XS GIS Cut Line= 3
      1712235.56      286244.394     1712304.108      285709.801
     1712346.541      285217.917
#Sta/Elev= 30
       0 1121.99    36.3 1117.32   110.1 1103.52     156 1091.47   191.9 1080.14
   227.9 1070.27   335.6 1048.78   371.5 1038.86   395.4 1033.13   419.4 1028.98
   443.3 1027.19   467.2 1022.06   503.2 1018.01   531.5 1013.76     539 1013.11
   546.5  1014.2   562.9 1017.32   574.8 1018.68   646.3 1024.48   670.2 1029.09
   729.7 1043.41   753.8 1050.27   860.8 1086.45   872.7 1088.69   896.6 1091.25
   908.5 1094.06   932.3 1103.26   944.2 1106.68   991.9 1117.37  1032.4 1127.53
#Mann= 3 , 0 , 0
       0      .1       0   531.5    .045       0   546.5      .1       0
Bank Sta=531.5,546.5
XS Rating Curve= 0 ,0
Exp/Cntr=0.3,0.1

Type RM Length L Ch R = 1 ,5877.7  ,302.997,309.236,317.042
XS GIS Cut Line= 3
     1712435.492      286309.012     1712669.749      285821.916
     1712862.967      285367.878
#Sta/Elev= 30
       0 1094.67      59 1083.83     138 1064.29     240 1043.83   296.1 1030.63
   348.8 1019.35     370 1017.61   401.5 1019.92   427.9 1019.84   480.6 1015.07
     533    1009   542.5 1008.76     548 1009.02   587.8 1012.25     615 1015.22
   633.1 1018.31   675.4 1028.54   688.3 1030.93   701.2 1032.21   714.1 1032.65
   741.7 1032.56   765.7 1031.71   777.9 1032.44   791.5 1034.09   843.1 1042.26
   894.7 1054.21   927.8  1060.7   972.1 1067.78   995.1 1069.88  1033.9 1075.43
#Mann= 3 , 0 , 0
       0      .1       0     533    .045       0     548      .1       0
Bank Sta=533,548
XS Rating Curve= 0 ,0
Exp/Cntr=0.3,0.1

Type RM Length L Ch R = 1 ,5568.4  ,494.322,490.764,488.808
XS GIS Cut Line= 3
     1712561.894      286405.463     1712898.044      286024.347
     1713238.536      285659.628
#Sta/Elev= 30
       0    1077    33.4 1067.77   105.2 1044.68   123.1 1040.99   205.8 1026.64
   230.8 1023.55   284.6 1019.01   348.8 1016.84   441.3 1015.59   468.6  1014.5
   484.5 1012.95   496.6 1009.92   500.3 1009.04   508.2 1010.16   511.6 1011.67
   525.4 1018.91   532.6 1021.97   548.8 1025.96   597.5 1036.43   662.5 1049.37
     695 1054.84   727.5 1059.47   743.7 1062.56   761.3 1068.72   785.8 1081.41
   794.2  1085.2   808.7  1089.9   922.4  1114.3   962.2 1125.88  1007.1 1140.37
#Mann= 3 , 0 , 0
       0      .1       0   496.6    .045       0   511.6      .1       0
Bank Sta=496.6,511.6
XS Rating Curve= 0 ,0
Exp/Cntr=0.3,0.1

Type RM Length L Ch R = 1 ,5077.7  ,398.78,400,393.293
XS GIS Cut Line= 3
     1712955.061       286803.98     1713221.967      286383.541
     1713537.601      285977.046
#Sta/Elev= 30
       0 1065.15   100.8 1061.77     143  1058.3   157.1 1054.93   171.1 1049.48
   199.2  1037.2   213.3 1032.01   269.6  1015.5   283.6  1013.6   353.9 1014.35
   396.1 1013.84   415.2 1012.59   490.5 1005.01   494.6 1004.86   505.5 1006.48
   524.4 1014.76     532 1016.68   548.9 1018.59   574.3 1019.97     642 1035.54
   677.3 1046.93   696.7 1055.26   719.8 1066.27   734.8 1072.71   754.8 1080.16
   774.1  1086.6   840.1  1102.8   915.2 1123.03   945.3 1129.76  1012.7 1143.39
#Mann= 3 , 0 , 0
       0      .1       0   490.5    .045       0   505.5      .1       0
Bank Sta=490.5,505.5
XS Rating Curve= 0 ,0
Exp/Cntr=0.3,0.1

Type RM Length L Ch R = 1 ,4677.7  ,520.063,508.52,502.894
XS GIS Cut Line= 3
     1713289.482      286966.008     1713587.688      286543.672
     1713764.302      286078.484
#Sta/Elev= 30
       0 1079.32    32.5 1069.54      99 1044.82   114.8 1040.48   139.6 1037.99
   157.2    1038   186.3  1040.8   215.3 1045.87   229.9 1046.45   360.7 1041.41
   389.7 1034.67   447.9 1012.14   462.4 1007.89   488.9 1006.38   509.5 1000.85
   520.1  999.71   524.5 1001.01   532.8 1003.48   569.5 1021.39   596.3 1028.58
   647.1 1037.84   689.2 1038.47   697.9 1039.23   707.6 1042.24   723.3 1052.41
   761.4 1085.87   774.1 1094.17   781.2 1097.09   836.4 1114.13  1014.6 1163.12
#Mann= 3 , 0 , 0
       0      .1       0   509.5    .045       0   524.5      .1       0
Bank Sta=509.5,524.5
XS Rating Curve= 0 ,0
Exp/Cntr=0.3,0.1

Type RM Length L Ch R = 1 ,4169.1  ,291.266,291.48,290.146
XS GIS Cut Line= 3
      1713875.95      287386.673     1713923.959      286917.824
     1713988.452      286368.919
#Sta/Elev= 30
       0 1078.38   112.9 1065.13   145.4 1060.26     182 1052.51   229.7 1035.68
   277.4 1023.13   307.7 1021.05     349 1019.93     361 1017.47   408.7 1002.99
   432.6  996.86     478  992.99   480.9  992.89     493  993.76   504.3  997.81
   516.2 1003.52   540.1 1011.71     564 1014.86   611.8 1024.61   707.5 1025.27
   755.3 1022.33   767.2 1023.13   791.2 1031.61   862.9 1062.16   886.8 1070.22
   910.7 1076.59   940.3 1082.13   982.4 1086.26  1006.3 1087.27    1024 1089.84
#Mann= 3 , 0 , 0
       0      .1       0     478    .045       0     493      .1       0
Bank Sta=478,493
XS Rating Curve= 0 ,0
Exp/Cntr=0.3,0.1

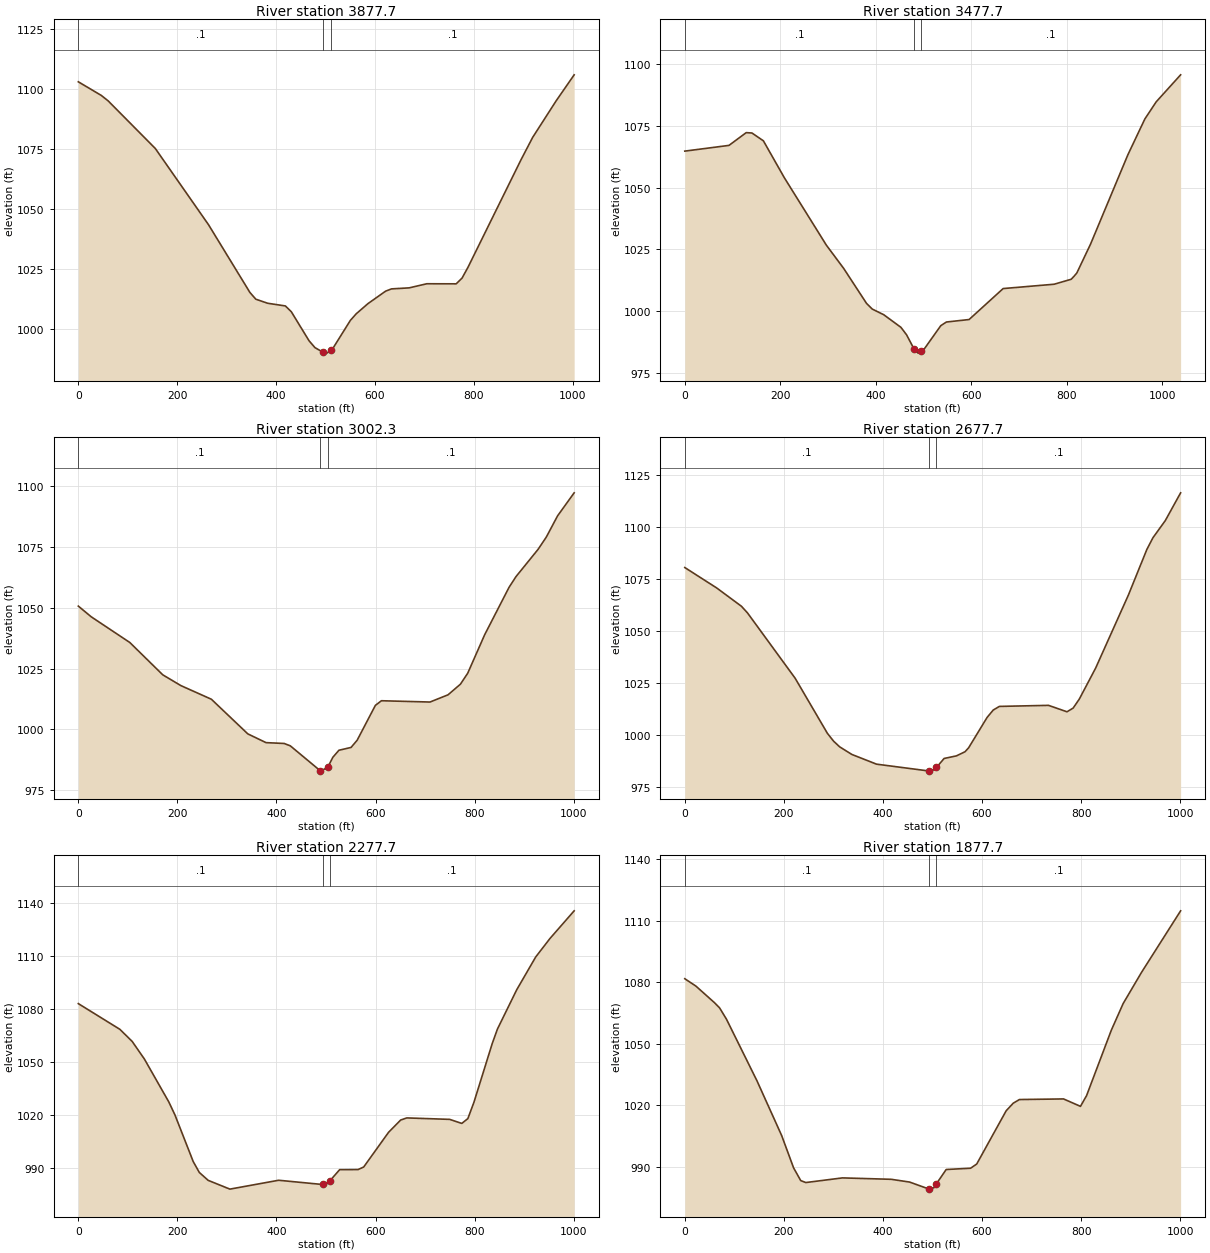
Type RM Length L Ch R = 1 ,3877.7  ,405.928,400,399.021
XS GIS Cut Line= 3
     1714156.032      287419.515     1714216.586      286920.426
     1714245.461      286420.995
#Sta/Elev= 30
       0 1103.04    46.6 1097.33    60.2  1095.1   155.6 1075.22   263.3 1043.38
     347 1015.11   358.9 1012.31   382.9 1010.61   418.7 1009.49   430.7 1007.07
   466.6  994.94   478.5   992.1   495.2   990.1   502.5   989.8   510.2  991.01
   514.4  991.67     550 1003.44   561.9 1006.21   585.7 1010.47   621.4 1015.67
   633.3 1016.61     669 1017.04   704.6 1018.75   764.1 1018.72     776 1021.14
   787.9 1025.62   894.9  1070.4   918.7 1079.84   966.3 1095.13  1002.6 1105.95
#Mann= 3 , 0 , 0
       0      .1       0   495.2    .045       0   510.2      .1       0
Bank Sta=495.2,510.2
XS Rating Curve= 0 ,0
Exp/Cntr=0.3,0.1

Type RM Length L Ch R = 1 ,3477.7  ,466.238,475.396,481.026
XS GIS Cut Line= 3
     1714660.155      287499.132      1714589.71      287016.909
     1714580.387      286465.956
#Sta/Elev= 30
       0  1064.7    92.6 1067.02   128.6 1072.16   140.6 1072.02   164.6 1068.86
   208.6 1053.92   296.6 1026.71   332.6  1017.4   380.6 1003.24   392.6 1000.94
   416.6  998.67   452.6  993.58   464.6  990.51   479.8  984.95   488.6  983.16
   494.8  983.85   500.4  984.55   536.1  994.24   547.9  995.72   595.4  996.72
   666.7 1009.22   773.5 1010.97   809.2 1012.97   815.4 1014.23     821  1015.5
   849.8 1027.18   927.9 1063.21   963.5 1077.68   987.3 1084.61  1038.4  1095.5
#Mann= 3 , 0 , 0
       0      .1       0   479.8    .045       0   494.8      .1       0
Bank Sta=479.8,494.8
XS Rating Curve= 0 ,0
Exp/Cntr=0.3,0.1

Type RM Length L Ch R = 1 ,3002.3  ,323.704,324.604,325.503
XS GIS Cut Line= 3
     1714925.621      287513.175     1715050.887      287028.605
     1715176.154      286544.034
#Sta/Elev= 30
       0  1050.7      26 1046.31     104 1035.73   170.5 1022.44   207.3 1017.99
   268.6 1012.41   342.2  998.16   378.9  994.57   415.7  994.22     428  993.24
   488.7  982.96   489.3  982.85   503.7  984.49   513.8  988.53   526.1  991.43
   550.6  992.59   562.9  995.55   599.7 1009.89   611.9 1011.79     710 1011.26
   746.4 1014.23   771.4  1018.6   786.1  1023.1   820.4 1038.95   869.5  1058.4
   883.5 1062.81   928.3 1074.07   944.9 1079.13   967.6 1087.83    1001 1097.28
#Mann= 3 , 0 , 0
       0      .1       0   488.7    .045       0   503.7      .1       0
Bank Sta=488.7,503.7
XS Rating Curve= 0 ,0
Exp/Cntr=0.3,0.1

Type RM Length L Ch R = 1 ,2677.7  ,400.503,400,399.497
XS GIS Cut Line= 3
     1715217.632      287600.033     1715362.167      287120.856
     1715506.702       286641.68
#Sta/Elev= 30
       0 1080.62    64.7 1070.73   114.3 1061.96   126.7 1058.71   222.8 1027.25
   287.9 1000.69   300.3  996.94   312.7  994.17   337.2  990.52   387.1  985.83
     493  982.53   498.7  982.47     508  984.22   523.5  988.57   548.3  989.82
   565.8  991.82   573.1  993.75   610.3 1008.35   622.7 1011.92   635.1 1013.67
   734.3 1014.18   771.6 1011.08     784 1012.86   796.4 1017.18   829.4 1032.13
   895.6 1067.38   932.8 1089.33   945.2 1095.02     970 1103.23    1001 1116.64
#Mann= 3 , 0 , 0
       0      .1       0     493    .045       0     508      .1       0
Bank Sta=493,508
XS Rating Curve= 0 ,0
Exp/Cntr=0.3,0.1

Type RM Length L Ch R = 1 ,2277.7  ,400,400,400
XS GIS Cut Line= 3
     1715612.652      287714.088     1715746.447      287231.803
     1715880.242      286749.517
#Sta/Elev= 30
       0 1083.18    83.9 1068.59   108.7 1061.74   133.4 1051.73   182.6 1027.44
     195 1020.07   231.9  993.61   244.2  987.41   262.1  982.92     306  977.94
   404.4  982.97     493  980.57     503  981.19     508  982.68   527.6  988.99
   564.6  989.03   576.1  990.48   626.2 1010.13   650.8 1017.15   663.2 1018.34
   749.7 1017.51   774.1 1015.22   786.4 1017.95   798.7 1027.24   835.7 1060.61
   846.1 1068.74   884.9 1090.96   923.3 1109.61   952.2 1120.13    1001 1135.82
#Mann= 3 , 0 , 0
       0      .1       0     493    .045       0     508      .1       0
Bank Sta=493,508
XS Rating Curve= 0 ,0
Exp/Cntr=0.3,0.1

Type RM Length L Ch R = 1 ,1877.7  ,582.916,584.01,585.103
XS GIS Cut Line= 3
     1715998.095      287821.017      1716131.89      287338.732
     1716265.685      286856.447
#Sta/Elev= 30
       0 1081.65    22.5 1078.04    59.5 1070.05    70.1 1067.48    84.2 1061.88
   145.8  1031.8   195.5 1005.17   219.7  989.34   234.1  983.15   244.3   982.2
   318.3  984.47   416.8  983.78   453.8  982.44     493  979.03   494.5  978.99
   503.1   979.7     508  981.61   527.7  988.56     577  989.19   589.3  991.23
   648.8 1017.22   663.2 1020.95   675.6  1022.7   764.6    1023   798.8 1019.38
   811.1  1024.6     861 1056.48     885 1069.54     922 1084.73    1001 1114.78
#Mann= 3 , 0 , 0
       0      .1       0     493    .045       0     508      .1       0
Bank Sta=493,508
XS Rating Curve= 0 ,0
Exp/Cntr=0.3,0.1

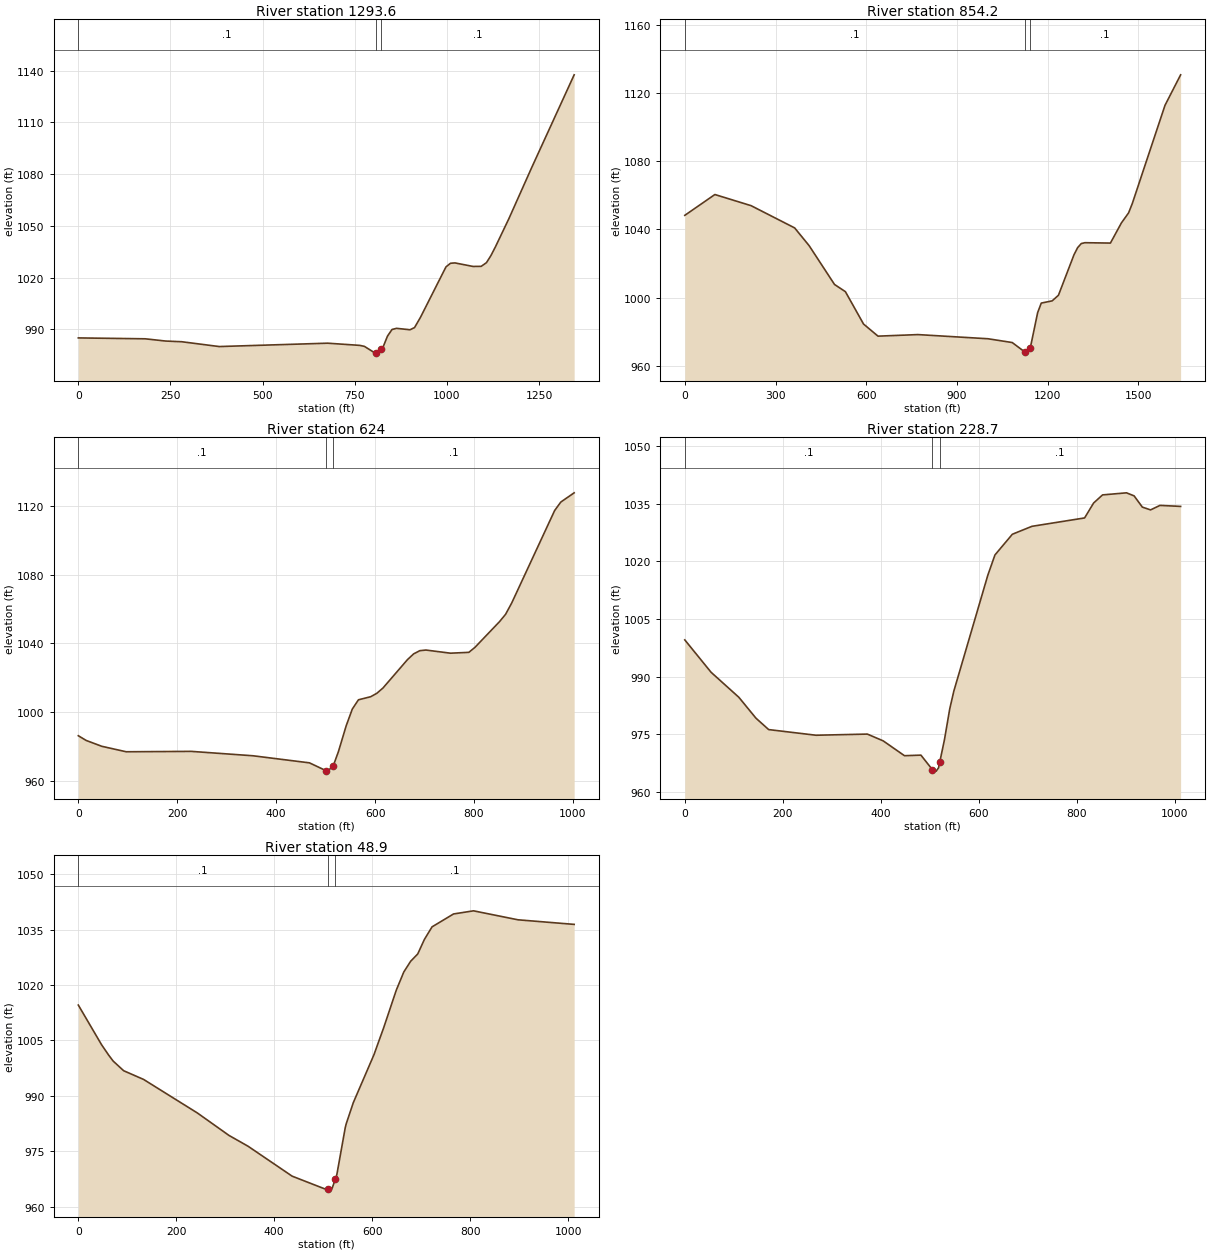
Type RM Length L Ch R = 1 ,1293.6  ,443.438,439.439,435.838
XS GIS Cut Line= 4
     1716211.004      288095.755       1716607.3      287755.462
     1716708.389      287449.398     1716822.953      286962.186
#Sta/Elev= 30
       0  985.07   181.7  984.55   236.4  983.26   280.7  982.85   382.2  980.06
   676.2  982.01   763.8  980.74   776.3  980.15   801.3  976.79   807.3  976.59
   813.8  976.25   822.3  978.54   826.3  979.51   838.8  986.13   851.1  989.96
   863.3  990.62   899.9   989.8   912.1  991.05   928.3  997.03   997.5 1026.27
  1009.7 1028.35  1021.9 1028.55  1070.7 1026.51  1092.9 1026.55  1107.3  1028.7
  1119.5 1032.85  1131.7 1037.91  1168.2 1054.24  1229.2 1083.44  1345.2  1137.6
#Mann= 3 , 0 , 0
       0      .1       0   807.3    .045       0   822.3      .1       0
Bank Sta=807.3,822.3
XS Rating Curve= 0 ,0
Exp/Cntr=0.3,0.1

Type RM Length L Ch R = 1 ,854.2   ,227.094,230.247,233.234
XS GIS Cut Line= 3
      1716969.39      288681.345     1717130.512      287553.891
     1717212.839      287059.728
#Sta/Elev= 30
       0  1048.3    99.5 1060.51   219.2 1053.98   363.3 1040.93   411.3  1030.5
   495.2 1007.75   531.2 1003.53   591.2  984.54     639  977.44   771.1  978.35
  1002.8  975.91  1082.9  973.69  1126.1  967.97  1130.9  967.48  1141.1  970.22
  1142.9  970.69    1167  991.21    1179  996.83  1215.1  998.14  1235.8 1001.42
  1287.3 1025.21  1299.4 1029.38  1311.4 1031.75  1323.4 1032.25  1407.7 1032.03
  1443.8 1043.78  1467.9 1049.78  1479.9 1055.14  1588.2 1112.82  1639.9 1130.72
#Mann= 3 , 0 , 0
       0      .1       0  1126.1    .045       0  1141.1      .1       0
#XS Ineff= 2 , 0
          755.71  978.05
Permanent Ineff=
       F       F
Bank Sta=1126.1,1141.1
XS Rating Curve= 0 ,0
Exp/Cntr=0.3,0.1

Type RM Length L Ch R = 1 ,624     ,382.951,395.225,406.44
XS GIS Cut Line= 3
     1717215.101       288094.21     1717353.178      287611.151
     1717497.227       287132.18
#Sta/Elev= 30
       0  986.14    15.7  983.41    47.4  979.99    96.8   976.8   228.3  977.03
   353.1  974.47   467.3  970.35   500.6  965.81   504.3  965.53   515.6   968.8
   525.8  976.87   541.5  991.92   553.9 1001.67   566.3 1007.06   591.1 1008.86
   603.5 1010.84   615.9 1013.93   665.5 1030.47   677.9  1033.8   690.3 1035.65
   702.7 1036.03   752.3  1034.2   789.5 1034.69   801.9 1037.61   851.5 1052.56
   863.8 1056.85   876.2 1063.45     963 1117.28   975.4 1122.19  1002.4 1127.57
#Mann= 3 , 0 , 0
       0      .1       0   500.6    .045       0   515.6      .1       0
Bank Sta=500.6,515.6
XS Rating Curve= 0 ,0
Exp/Cntr=0.3,0.1

Type RM Length L Ch R = 1 ,228.7   ,176.317,179.825,183.403
XS GIS Cut Line= 3
     1717296.274      288170.811     1717674.737      287822.242
     1718027.848      287471.042
#Sta/Elev= 30
       0  999.58    53.7  991.16   110.3  984.67   145.3  979.23   171.3  976.26
     268  974.79   372.8  975.09   405.1  973.33   448.6  969.47   482.2  969.62
   505.5  965.86   513.4  965.46   518.2  966.33   520.5  967.73   530.2   973.6
     541  981.63   549.4  986.27   618.7 1016.36   633.3 1021.66   668.9 1027.05
   708.9 1029.11   816.4 1031.29   834.8 1035.17   853.1 1037.28     902 1037.82
   917.5 1037.03   934.3 1034.11   951.1 1033.38   970.3 1034.55  1012.5 1034.29
#Mann= 3 , 0 , 0
       0      .1       0   505.5    .045       0   520.5      .1       0
Bank Sta=505.5,520.5
XS Rating Curve= 0 ,0
Exp/Cntr=0.3,0.1

Type RM Length L Ch R = 1 ,48.9    ,48.253,48.907,50.32
XS GIS Cut Line= 3
      1717328.94      288265.949     1717757.934      287981.873
     1718162.314      287691.175
#Sta/Elev= 30
       0 1014.57    47.6 1003.81    61.9 1001.04    71.1  999.42    92.6   996.8
   133.1  994.46   243.1  985.37   307.6   979.3   346.7  976.36   436.6  968.27
   502.4  964.87   509.8  964.84   517.6  964.76   524.8   967.4     528  968.76
   545.1  981.42   546.9  982.38   561.5  988.16   603.6 1001.11   623.9 1008.58
   649.2 1018.58   664.6 1023.52   678.5 1026.41   693.1 1028.41   706.7 1032.34
   722.3 1035.74   766.2 1039.23     807 1040.08   897.8 1037.65  1012.5 1036.41
#Mann= 3 , 0 , 0
       0      .1       0   509.8    .045       0   524.8      .1       0
Bank Sta=509.8,524.8
XS Rating Curve= 0 ,0
Exp/Cntr=0.3,0.1

Chan Stop Cuts=-1
Use User Specified Reach Order=0